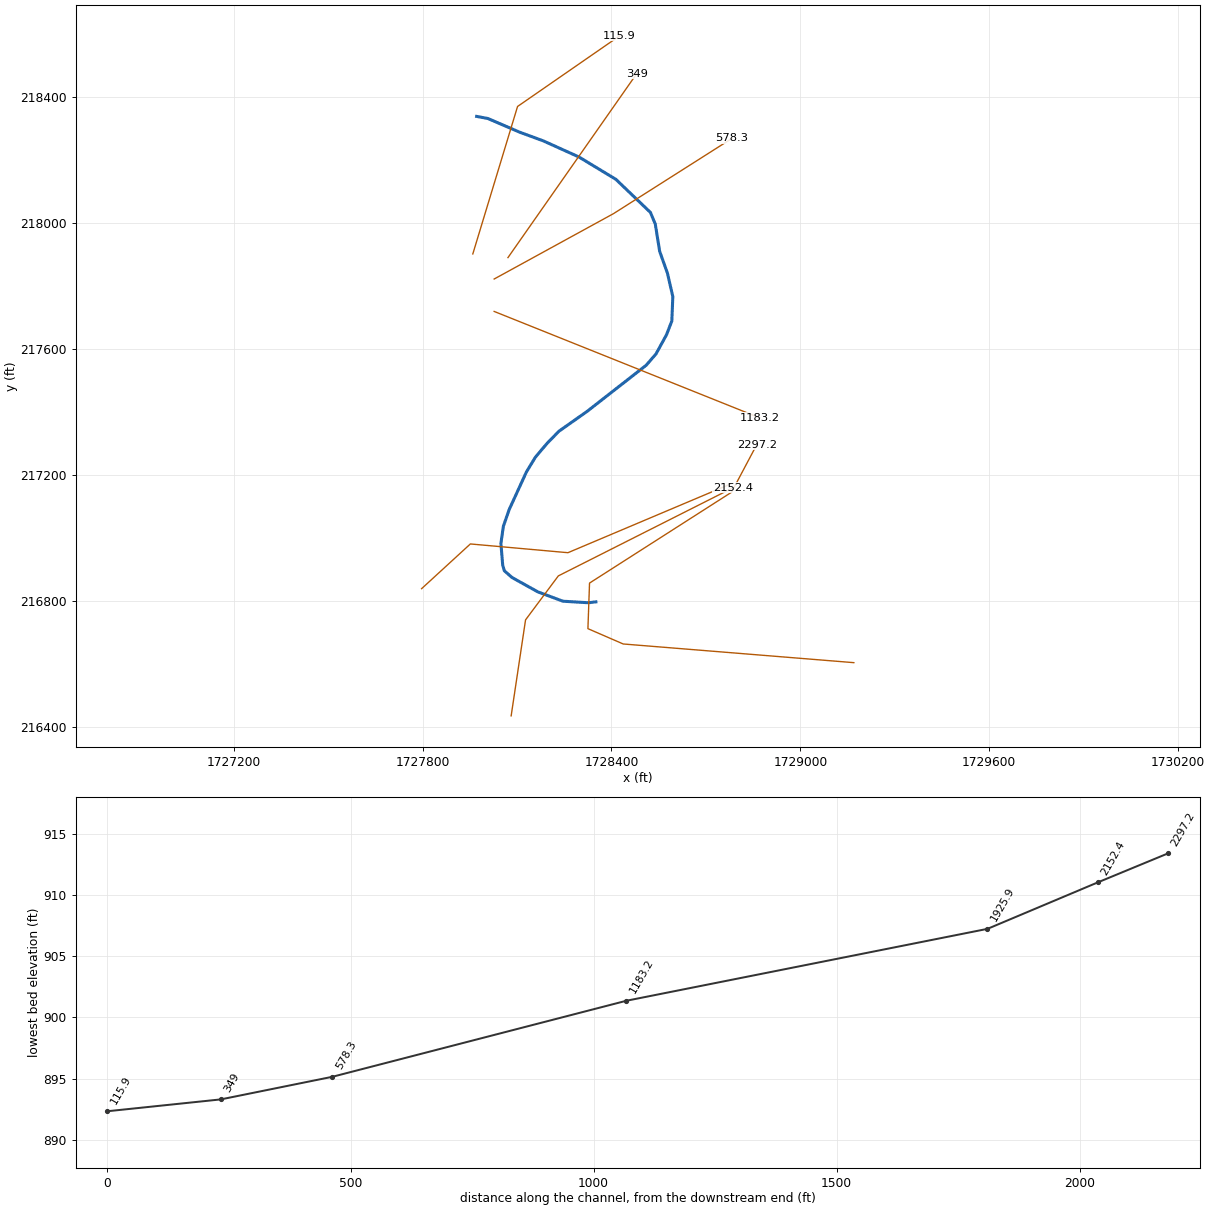
--- lttlhffcrk.prj (project) ---

Proj Title=lttlhffcrk
Current Plan=p01
Default Exp/Contr=0,0
English Units
Geom File=g01
Flow File=f01
Plan File=p01
BEGIN DESCRIPTION:
END DESCRIPTION:
DSS Export Rating Curves= 0
DSS Export Rating Curve Sorted= 0
DSS Export Volume Flow Curves= 0
DXF OffsetX= 0
DXF OffsetY= 0
DXF ScaleX= 0
DXF ScaleY= 0

--- lttlhffcrk.p01 (plan) ---

Plan Title=Approximate Study - 100yr
Program Version=4.00
Geom File=g01
Flow File=f01
Subcritical Flow
K Sum by GR= 0
Std Step Tol= 0.01
Critical Tol= 0.01
Num of Std Step Trials= 20
Max Error Tol= 0.3
Flow Tol Ratio= 0.001
Split Flow NTrial= 30
Split Flow Tol= 0.02
Split Flow Ratio= 0.02
Log Output Level= 0
Friction Slope Method= 1
Unsteady Friction Slope Method= 2
Unsteady Bridges Friction Slope Method= 1
Parabolic Critical Depth
Global Vel Dist= 0 , 0 , 0
Global Log Level= 0
CheckData=True
Encroach Param=-1 ,0,0, 0
Run HTab= 0
Run UNet= 0
Run PostProcess= 0
Run WQNet= 0
UNET Theta= 0
UNET Theta Warmup= 0
UNET ZTol= 0
UNET ZSATol= 0
UNET MxIter= 0
UNET MaxInSteps= 0
UNET DtIC= 0
UNET DtMin= 0
UNET MaxCRTS= 0
UNET WFStab= 0
UNET SFStab= 0
UNET WFX= 1
UNET SFX= 1
UNET DSS MLevel= 1
UNET DZMax Abort= 0
UNET Convert EG Bridges= 0
UNET Use Existing IB Tables= 0
UNET Froude Reduction=False
UNET Froude Limit= 0
UNET Froude Power= 0
UNET Time Slicing=0,0, 5
Write IC File= 0
Echo Input=False
Echo Output=False
Write Detailed= 0
Detailed Automatic Start=False, 0
WQ ULTIMATE=-1
WQ Max Comp Step=1HOUR
WQ Output Interval=15MIN
WQ Output Selected Increments= 0
WQ Output face flow=0
WQ Output face velocity=0
WQ Output face area=0
WQ Output face dispersion=0
WQ Output cell volume=0
WQ Output cell surface area=0
WQ Output cell continuity=0
WQ Output face conc=0
WQ Output face dconc_dx=0
WQ Output face courant=0
WQ Output face peclet=0
WQ Output face adv mass=0
WQ Output face disp mass=0
WQ Output cell mass=0
WQ Output cell source sink temp=0
WQ Output cell source sink nsm=0
WQ Output MaxMinRange=-1
WQ Daily Max Min Mean=-1
WQ Daily Range=0
WQ Daily Time=0
WQ Create Restart=0
WQ Fixed Restart=0
WQ System Summary=False
Sorting and Armoring Iterations= 10
XS Update Threshold= 0.02
Hydraulics Update Threshold= 0.02
Energy Slope Method= 1
Volume Change Method= 0
XS Weighting Method= 0
Number of US Weighted Cross Sections= 1
Number of DS Weighted Cross Sections= 1
Upstream XS Weight=0.25
Main XS Weight=0.5
Downstream XS Weight=0.25
Number of DS XS's Weighted with US Boundary= 1
Upstream Boundary Weight= 1
Weight of XSs Associated with US Boundary= 0
Number of US XS's Weighted with DS Boundary= 1
Downstream Boundary Weight= 0.5
Weight of XSs Associated with DS Boundary= 0.5
Sediment Output Level= 4
Mass or Volume Output= 0
Output Increment Type= 1
Profile and TS Output Increment= 10
XS Output Flag= 0
XS Output Increment= 10
Disregard all LS=0
Disregard all Conn=0
Disregard all Breaches=0
Disregard all Pumps=0

--- lttlhffcrk.f01 (steady flow) ---

Flow Title=USGS Regression Equation
Program Version=4.00
Number of Profiles= 1
Profile Names=P100yr
River Rch & RM=lttlhffcrk,Main            ,2297.2
    5768
River Rch & RM=lttlhffcrk,Main            ,115.9
    5773
Boundary for River Rch & Prof#=lttlhffcrk,Main            , 1
Up Type= 0
Dn Type= 3
Dn Slope=0.007505
DSS Import GetInterval= 0
DSS Import GetPeak= 0
DSS Import FillOption= 0

--- lttlhffcrk.g01 (geometry) ---

Geom Title=USGS 3m DEM
Program Version=4.00

River Reach=lttlhffcrk      ,Main
Reach XY= 30
     1728350.432      216796.093     1728327.138      216793.188
     1728245.772      216798.067     1728165.794      216827.901
     1728083.966       216873.44     1728059.675      216894.718
     1728054.487        216912.1     1728048.748      216981.742
     1728056.469      217035.758     1728074.967      217089.067
     1728130.007      217209.137      1728158.55      217255.947
     1728195.419      217299.507     1728233.117      217338.055
     1728322.863      217401.287     1728510.401      217547.765
     1728541.518      217583.747     1728574.898      217644.676
     1728591.722      217688.356     1728594.813      217765.647
     1728577.809      217839.846     1728553.077      217909.407
     1728539.164      217995.973     1728523.706      218033.072
     1728413.954      218138.187     1728296.472      218209.295
     1728183.628      218260.306     1728107.883      218288.131
     1728007.405      218331.413     1727971.713      218338.127

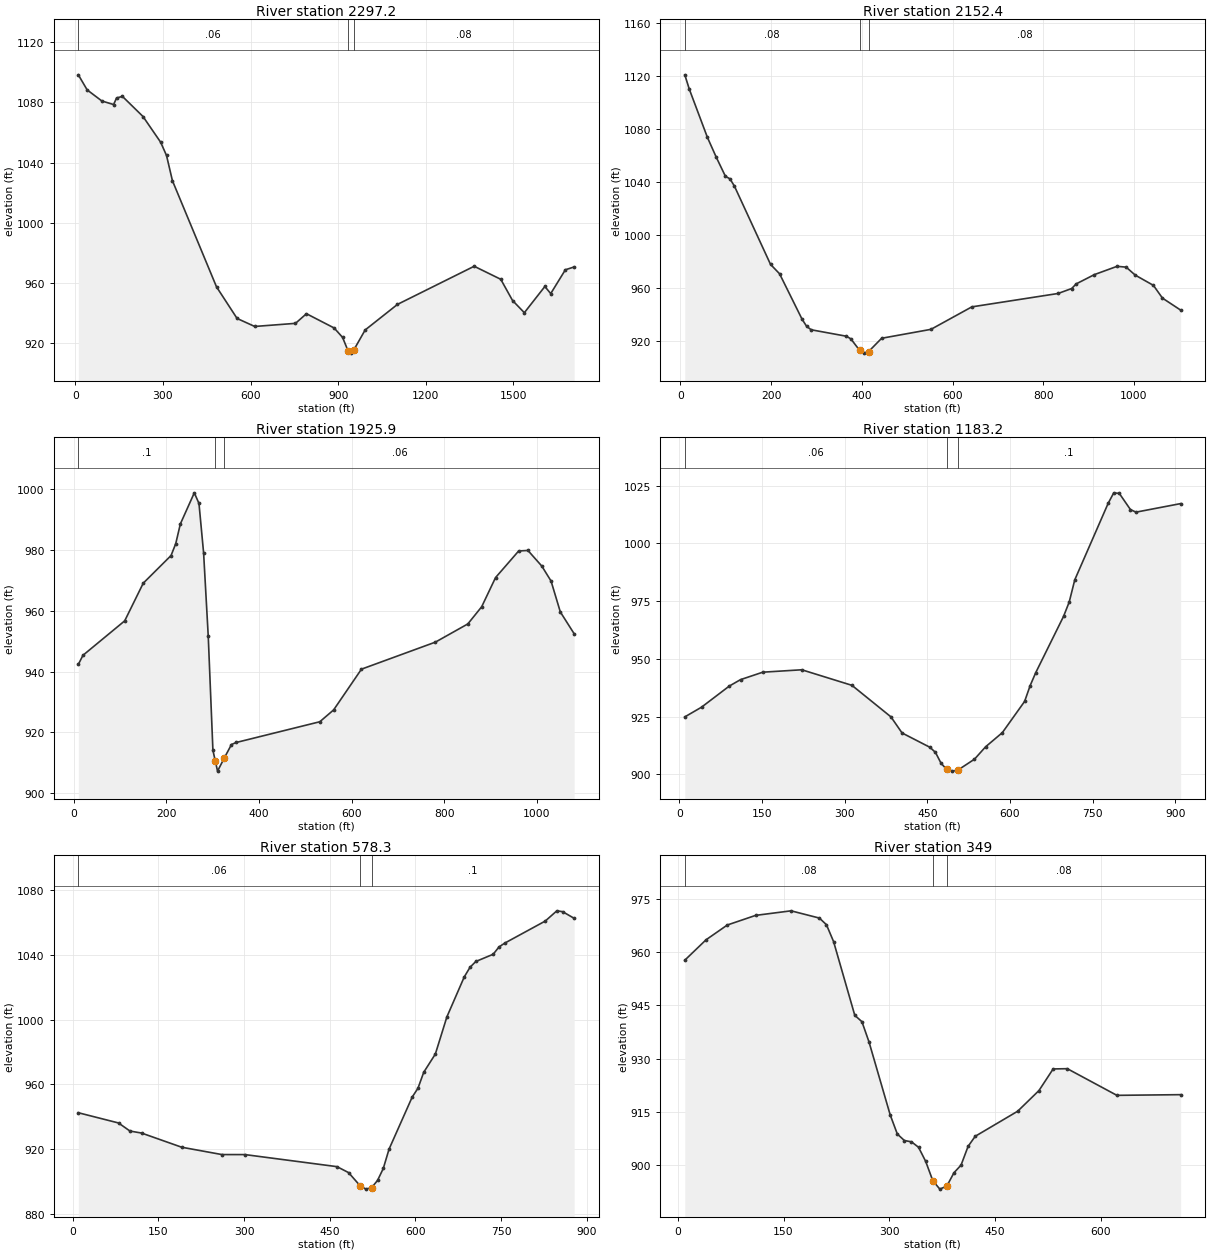
Type RM Length L Ch R = 1 ,2297.2  ,160.1,144.7,129.3
XS GIS Cut Line= 6
      1729169.87      216602.892     1728437.273      216662.223
     1728325.177      216710.861     1728330.258      216855.656
     1728781.382      217144.278      1728861.29      217295.023
#Sta/Elev= 30
    10.1 1098.29    40.3 1088.29    90.6 1080.92   130.9 1078.55     141  1082.9
   161.1 1083.97   231.6  1070.6     292 1053.53   312.1 1044.73   332.3    1028
   483.3  957.47   553.8  936.47   614.2  931.15   753.8  933.22   791.4  939.62
   886.2  930.14   915.1  923.88   934.1  914.82   944.1  913.44   954.1  915.74
   992.4  928.82  1103.1  945.81  1365.8  971.14  1456.8  962.49  1497.2  948.39
  1537.6  940.29  1607.9   957.7  1627.9  952.97  1678.1   968.8  1708.2  970.69
#Mann= 3 , 0 , 0
    10.1     .06       0   934.1    .045       0   954.1     .08       0
Bank Sta=934.1,954.1
XS Rating Curve= 0 ,0
Exp/Cntr=0.3,0.1

Type RM Length L Ch R = 1 ,2152.4  ,252.3,226.5,200.8
XS GIS Cut Line= 4
     1728081.313      216433.972     1728127.037      216738.804
     1728231.188      216878.518     1728784.964      217157.946
#Sta/Elev= 30
     9.9 1121.21    19.9 1110.32    59.7    1074    79.5  1058.8    99.4 1044.62
   109.4 1042.67   119.3 1037.16   198.9  978.06   218.8  970.97   268.5  936.59
   278.4  931.33   288.4   928.7   366.3  923.81     376   921.8   395.1  913.22
   405.1  911.06   415.1  912.27   443.8  922.28   552.5  929.02   642.6  945.99
   832.7   956.1   862.7  959.85   872.7  963.36   912.7  970.35   962.7   976.6
   982.7     976  1002.7  969.98  1042.8  962.23  1062.8  952.59  1102.8  943.56
#Mann= 3 , 0 , 0
     9.9     .08       0   395.1    .045       0   415.1     .08       0
Bank Sta=395.1,415.1
XS Rating Curve= 0 ,0
Exp/Cntr=0.3,0.1

Type RM Length L Ch R = 1 ,1925.9  ,748.7,742.8,736.8
XS GIS Cut Line= 4
     1727796.804      216837.874     1727951.745      216979.972
     1728261.671      216952.185     1728776.813      217169.837
#Sta/Elev= 30
      10  942.34      20  945.33   110.1  956.65   150.2  969.04   210.2  978.12
   220.3  982.01   230.3  988.51   260.4  998.73   270.5  995.24   280.5  978.96
   290.5  951.63   300.6   914.1   305.6  910.68   310.6  907.26   325.6 911.717
   340.7  916.01   350.8  916.67   531.4  923.49   561.3  927.39   621.3  940.77
     781  949.66     851  955.64   880.9  961.28   910.9  970.88   960.8  979.62
   980.8  979.79  1010.7  974.66  1030.7  969.74  1050.7  959.59  1080.6  952.41
#Mann= 3 , 0 , 0
      10      .1       0   305.6    .045       0   325.6     .06       0
Bank Sta=305.6,325.6
XS Rating Curve= 0 ,0
Exp/Cntr=0.3,0.1

Type RM Length L Ch R = 1 ,1183.2  ,582.4,604.9,627.4
XS GIS Cut Line= 2
     1728027.257      217718.595     1728871.454      217380.313
#Sta/Elev= 30
    10.1  924.86    40.4  929.06    90.9  938.23   111.2     941   151.6  944.23
   222.3  945.27   313.3  938.53     384  924.88   404.2   917.9   454.7   911.7
   464.8  909.48   474.9  904.81   485.1   902.1   495.1  901.37   505.1  901.76
   535.6  906.55   555.8  911.92   586.1  918.04   626.5  931.57   636.6  938.44
   646.7  944.04   697.2  968.44   707.4  974.62   717.5  984.24   778.1 1017.39
   788.2 1021.92   798.3 1021.66   818.5 1014.66   828.6 1013.55   909.5 1017.25
#Mann= 3 , 0 , 0
    10.1     .06       0   485.1    .045       0   505.1      .1       0
Bank Sta=485.1,505.1
XS Rating Curve= 0 ,0
Exp/Cntr=0.3,0.1

Type RM Length L Ch R = 1 ,578.3   ,219.3,229.3,239.2
XS GIS Cut Line= 3
     1728027.298      217821.531     1728406.466      218029.255
     1728782.424      218268.039
#Sta/Elev= 30
    10.1  942.42    80.4  936.09   100.5  931.08   120.7  929.85     191  921.07
   261.4  916.53   301.6  916.52   462.7  909.05     483  905.36   503.3  897.17
   513.3  895.14   523.3  896.09   533.6   900.5   543.7  907.91   553.8  919.89
   594.3  952.13   604.4  957.58   614.5  967.48   634.8  978.74     655 1001.75
   685.4 1026.49   695.5 1032.46   705.6 1036.03     736 1040.51   746.1    1045
   756.3 1047.42   827.1 1061.05   847.4 1067.39   857.5 1066.87   877.7 1062.75
#Mann= 3 , 0 , 0
    10.1     .06       0   503.3    .045       0   523.3      .1       0
Bank Sta=503.3,523.3
XS Rating Curve= 0 ,0
Exp/Cntr=0.3,0.1

Type RM Length L Ch R = 1 ,349     ,225.2,233.1,241.1
XS GIS Cut Line= 2
     1728071.152      217889.541     1728480.133        218473.8
#Sta/Elev= 30
      10  957.71    40.2  963.46    70.3  967.61   110.5  970.32   160.7   971.6
   200.9  969.56   210.9  967.69     221  962.95   251.1  942.19   261.2  940.41
   271.2  934.74   301.3  914.18   311.4   908.8   321.4  906.97   331.5   906.6
   341.5  905.07   351.6  901.11   361.7  895.68   371.7  893.29   381.7  894.17
   391.7  897.89   401.8  900.05   411.8  905.33   421.9  908.16   482.1  915.21
   512.3  921.03   532.4  927.11   552.5  927.18   622.8  919.68   713.2  919.87
#Mann= 3 , 0 , 0
      10     .08       0   361.7    .045       0   381.7     .08       0
Bank Sta=361.7,381.7
XS Rating Curve= 0 ,0
Exp/Cntr=0.3,0.1

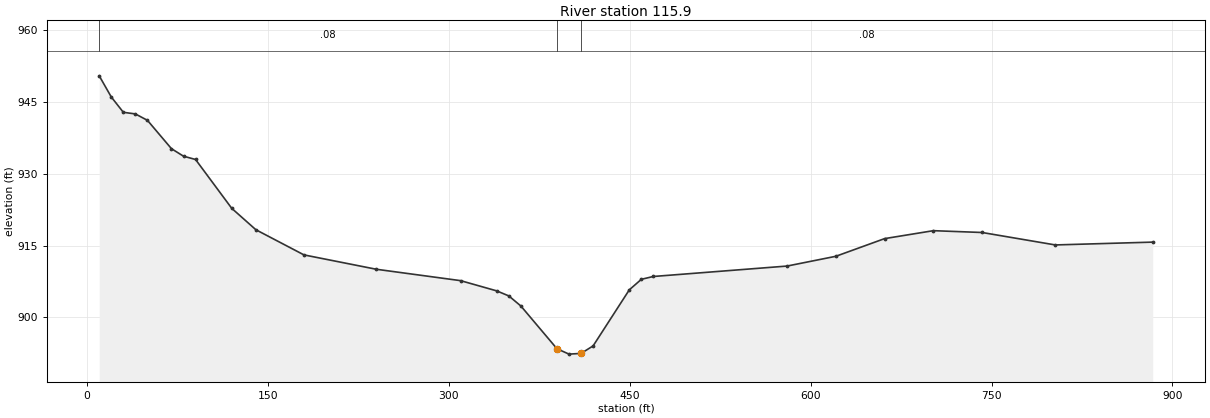
Type RM Length L Ch R = 1 ,115.9   ,113.2,115.9,118.6
XS GIS Cut Line= 3
     1727959.486      217901.217     1728101.635      218369.649
     1728425.818      218593.897
#Sta/Elev= 30
      10  950.46      20  946.04      30  942.84      40   942.5      50  941.16
    69.9  935.24    79.9  933.67    89.9  932.98   119.9  922.78   139.9  918.31
   179.8  913.05   239.8  910.05   309.7  907.67   339.7  905.53   349.7  904.48
   359.7  902.37   389.6  893.45   399.6  892.32   409.6  892.47   419.6  894.04
   449.6  905.75   459.6  907.95   469.5  908.54   580.5  910.72   620.9  912.76
   661.3  916.45   701.8  918.11   742.2  917.73   802.9  915.13   883.7  915.72
#Mann= 3 , 0 , 0
      10     .08       0   389.6    .045       0   409.6     .08       0
Bank Sta=389.6,409.6
XS Rating Curve= 0 ,0
Exp/Cntr=0.3,0.1

Chan Stop Cuts=-1
Use User Specified Reach Order=0